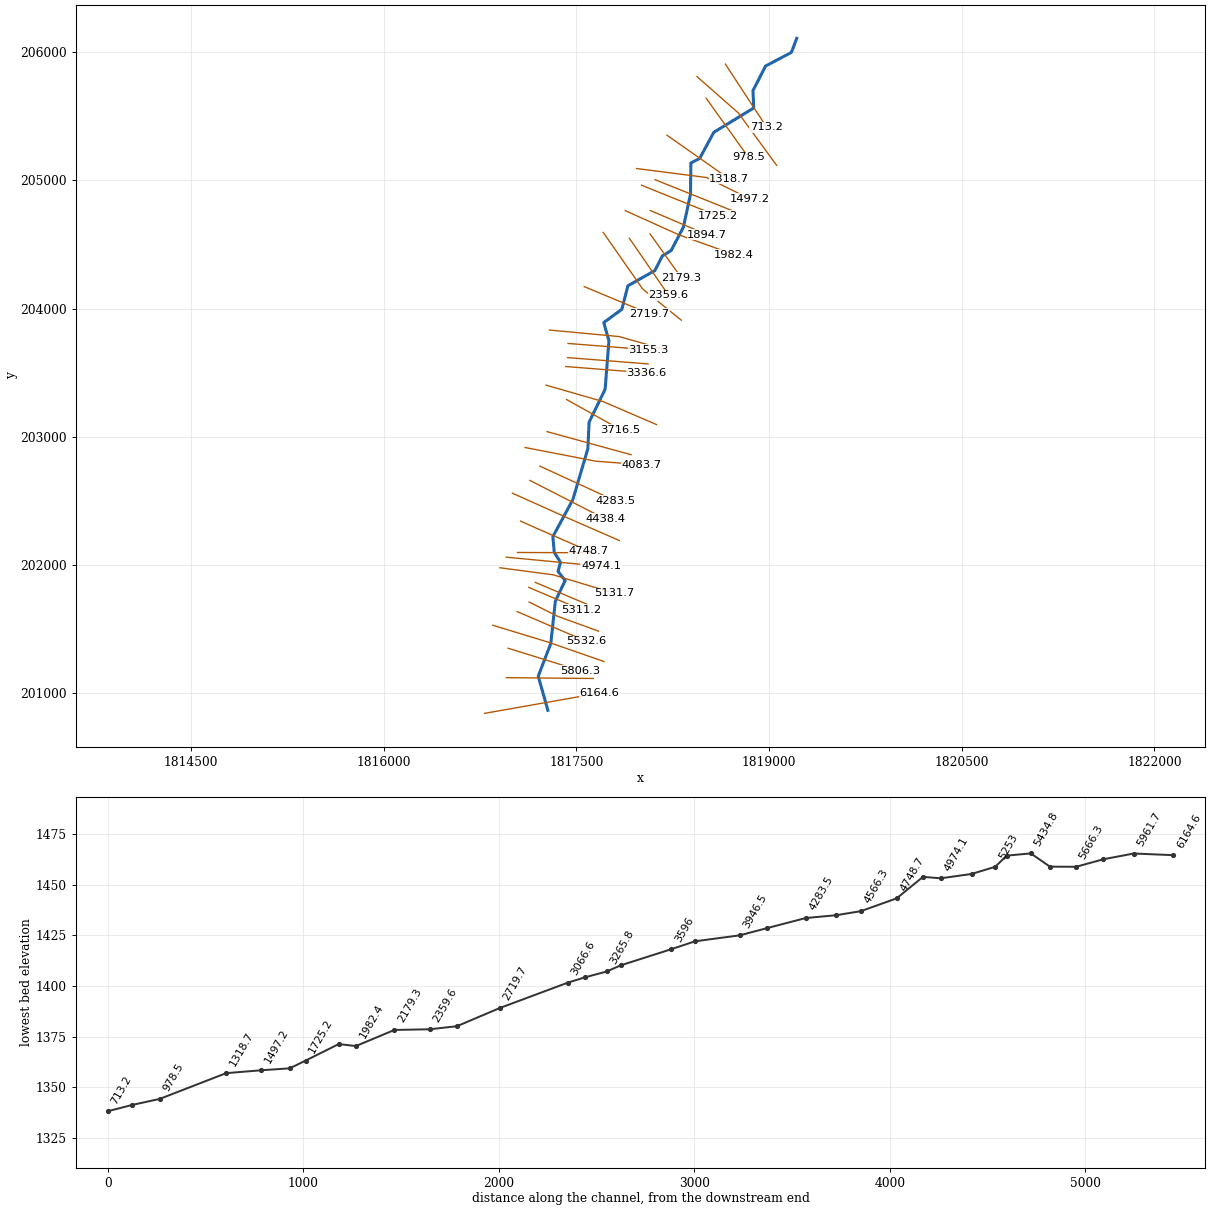
--- LambertBr1.prj (project) ---

Proj Title=LambertBr1
Current Plan=p01
Geom File=g01
Flow File=f01
Plan File=p01
DSS Export Rating Curves=0
DSS Export Rating Curve Sorted=0
DSS Export Volume Flow Curves=0
DXF OffsetX=0
DXF OffsetY=0
DXF ScaleX=0
DXF ScaleY=0

--- LambertBr1.p01 (plan) ---

Plan Title=Floodplain
Program Version=4.00
Geom File=g01
Flow File=f01
K Sum by GR=0
Std Step Tol=0.01
Critical Tol=0.01
Num of Std Step Trials=20
Max Error Tol=0.3
Flow Tol Ratio=0.001
Split Flow NTrial=30
Split Flow Tol=0.02
Split Flow Ratio=0.02
Log Output Level=0
Friction Slope Method=1
Unsteady Friction Slope Method=2
Unsteady Bridges Friction Slope Method=1
Global Log Level=0
CheckData=False
Run HTab=0
Run UNet=0
Run PostProcess=0
UNET Theta=0
UNET Theta Warmup=0
UNET ZTol=0
UNET ZSATol=0
UNET MxIter=0
UNET MaxInSteps=0
UNET DtIC=0
UNET DtMin=0
UNET MaxCRTS=0
UNET WFStab=0
UNET SFStab=0
UNET WFX=0
UNET SFX=0
UNET DSS MLevel=0
UNET DZMax Abort=0
UNET Convert EG Bridges=0
UNET Use Existing IB Tables=0
UNET Froude Limit=0
UNET Froude Power=0
Write IC File=0
Echo Input=False
Echo Output=False
Write Detailed=0

--- LambertBr1.f01 (steady flow) ---

Flow Title=NFF Regression Equation
Program Version=4.00
Number of Profiles=1
Profile Names=P100yr
River Rch & RM=LambertBr1,Main      ,6164.6
547.6594
River Rch & RM=LambertBr1,Main      ,5961.7
609.3717
River Rch & RM=LambertBr1,Main      ,4566.3
657.0565
River Rch & RM=LambertBr1,Main      ,2719.7
714.4248
River Rch & RM=LambertBr1,Main      ,219.6
780.3364
Boundary for River Rch & Prof#=LambertBr1,Main      ,1
Up Type=0
Dn Type=3
Dn Slope=0.024834

--- LambertBr1.g01 (geometry) ---

Geom Title=USGS 10m DEM
Program Version=4.00

River Reach=LambertBr1     ,Main
Reach XY= 30
     1817278.949      200866.067     1817204.143      201132.923
     1817301.966      201388.269     1817337.211      201718.422
     1817413.455      201878.103     1817358.070      201950.751
     1817377.491      202019.803     1817328.580      202098.924
     1817317.910      202221.083     1817473.379      202509.791
     1817590.280      202907.762     1817599.870      203113.957
     1817724.547      203370.023     1817754.277      203748.847
     1817713.997      203890.786     1817854.977      203994.363
     1817901.970      204177.542     1818112.002      204296.464
     1818169.545      204409.632     1818238.596      204452.789
     1818333.542      204634.049     1818389.167      204892.033
     1818392.044      205135.631     1818460.137      205170.157
     1818570.427      205374.434     1818881.159      205564.326
     1818875.405      205699.552     1818973.227      205891.361
     1819174.628      205997.816     1819216.028      206107.510

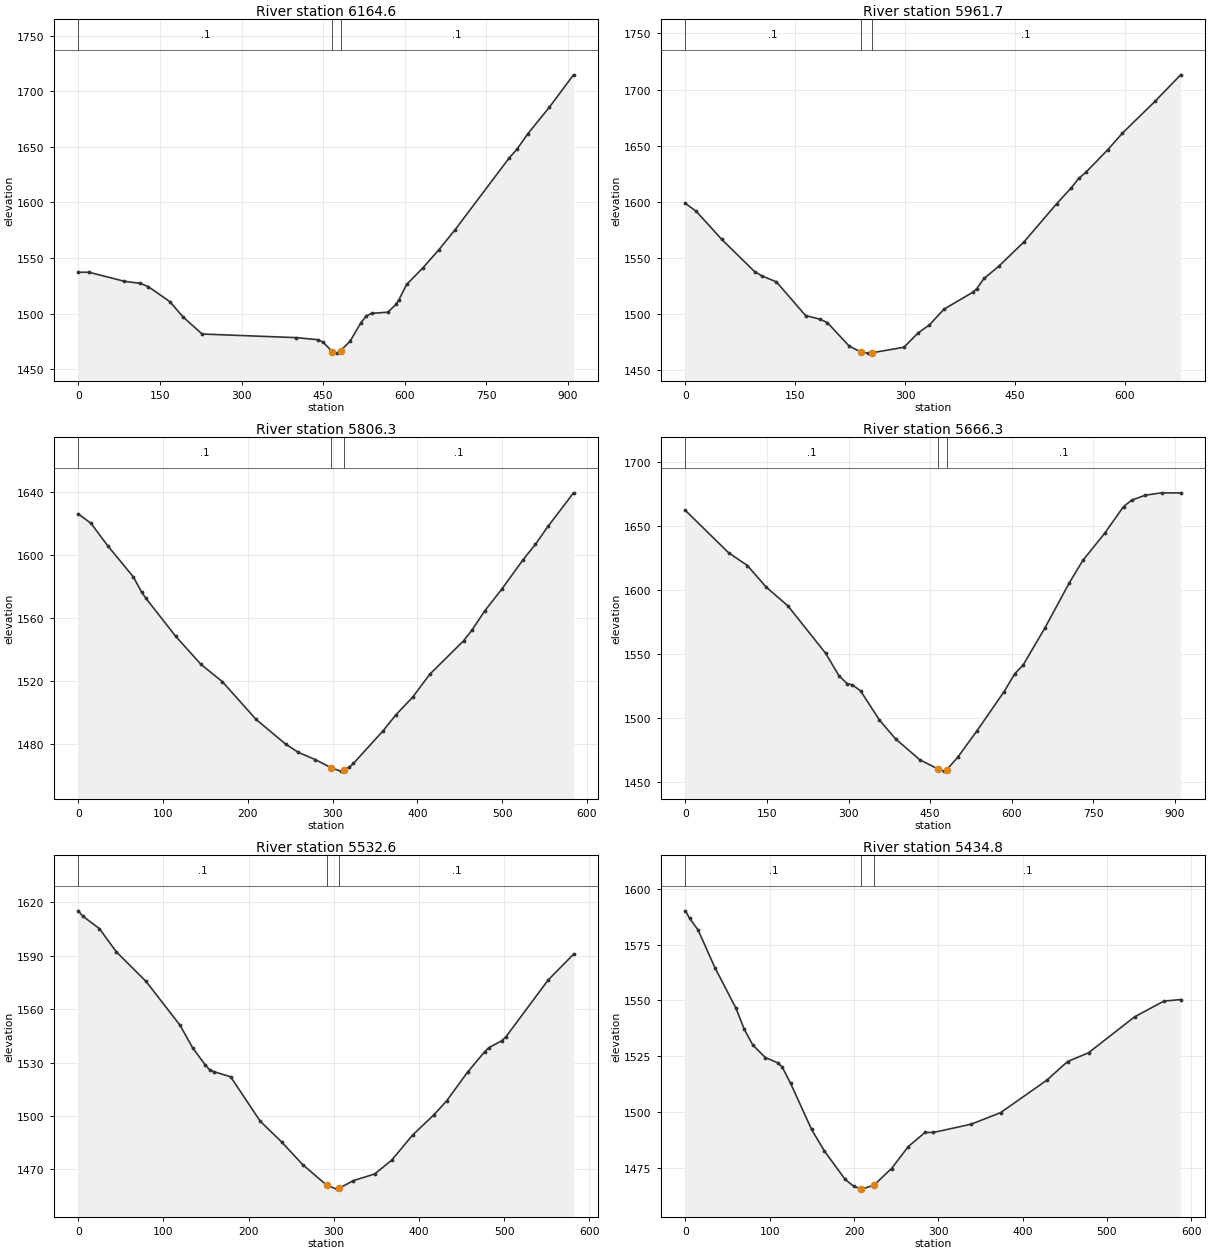
Type RM Length L Ch R = 1 ,6164.6,207.2,202.9,198.6
XS GIS Cut Line= 3
     1816785.518      200842.630     1817233.572      200921.834
     1817681.625      201001.038
#Sta/Elev= 30
       0 1537.31    19.8 1537.28    84.1 1529.23   113.8 1527.28   128.6 1524.36
   168.2 1510.87   192.9 1496.94   227.5 1481.77   400.6 1478.52   440.2 1476.67
   450.0 1474.42   466.8 1465.92   474.8 1464.60   481.8 1466.62   499.5 1475.38
   519.3 1491.94   529.2 1497.97   539.1 1500.34   568.8 1501.40   583.6 1508.32
   588.5 1511.95   603.4 1526.36   633.0 1541.16   662.7 1557.59   692.4 1575.50
   791.3 1639.73   806.1 1647.90   825.9 1661.64   865.5 1685.56   910.0 1714.71
#Mann= 3 , 0 , 0
       0     0.1       0   466.8   0.045       0   481.8     0.1       0
Bank Sta=   466.8,   481.8
Exp/Cntr=0.3,0.1

Type RM Length L Ch R = 1 ,5961.7,162.4,155.4,148.4
XS GIS Cut Line= 2
     1816956.729      201121.174     1817632.596      201114.737
#Sta/Elev= 30
       0 1598.67    14.9 1591.52    49.7 1566.56    94.4 1537.97   104.4 1534.16
   124.2 1528.81   164.0 1498.84   183.9 1495.57   193.8 1492.54   223.6 1471.63
   239.3 1466.50   248.5 1465.42   254.3 1465.70   298.2 1470.62   318.1 1483.72
   333.0 1490.51   352.9 1504.55   392.6 1519.73   397.6 1522.75   407.5 1531.84
   427.4 1542.56   462.2 1564.47   506.9 1598.55   526.8 1612.63   536.7 1620.87
   546.7 1626.44   576.5 1646.46   596.4 1661.17   641.1 1689.62   675.9 1713.07
#Mann= 3 , 0 , 0
       0     0.1       0   239.3   0.045       0   254.3     0.1       0
Bank Sta=   239.3,   254.3
Exp/Cntr=0.3,0.1

Type RM Length L Ch R = 1 ,5806.3,140.6,139.9,139
XS GIS Cut Line= 2
     1816969.602      201350.754     1817527.461      201176.959
#Sta/Elev= 30
       0 1626.19    15.0 1620.20    35.0 1605.73    64.9 1586.17    74.9 1576.27
    79.9 1572.46   114.9 1548.36   144.8 1530.45   169.8 1519.58   209.8 1495.46
   244.7 1479.76   259.7 1474.48   279.7 1469.93   298.6 1464.63   309.6 1462.59
   313.6 1463.28   319.6 1465.00   324.6 1467.49   359.6 1488.24   374.6 1498.34
   394.5 1509.62   414.5 1524.09   454.5 1545.46   464.4 1552.21   479.4 1564.41
   499.4 1578.17   524.4 1596.79   539.4 1606.92   554.3 1618.32   584.3 1639.60
#Mann= 3 , 0 , 0
       0     0.1       0   298.6   0.045       0   313.6     0.1       0
Bank Sta=   298.6,   313.6
Exp/Cntr=0.3,0.1

Type RM Length L Ch R = 1 ,5666.3,135.5,133.7,132.2
XS GIS Cut Line= 3
     1816850.397      201529.818     1817286.393      201396.763
     1817715.875      201246.985
#Sta/Elev= 30
       0 1662.43    79.3 1629.45   114.0 1619.43   148.6 1602.55   188.3 1588.01
   257.6 1551.05   282.4 1533.36   297.3 1527.22   307.2 1526.20   322.1 1521.53
   356.8 1498.74   386.5 1484.03   431.1 1467.70   465.1 1460.44   475.8 1458.86
   480.1 1459.73   500.8 1469.71   535.8 1490.15   585.8 1520.84   605.8 1535.00
   620.8 1541.58   660.8 1570.48   705.8 1605.82   730.8 1623.42   770.7 1644.47
   805.7 1665.49   820.7 1670.50   845.7 1674.35   875.7 1676.21   910.7 1676.14
#Mann= 3 , 0 , 0
       0     0.1       0   465.1   0.045       0   480.1     0.1       0
Bank Sta=   465.1,   480.1
Exp/Cntr=0.3,0.1

Type RM Length L Ch R = 1 ,5532.6,99.3,97.8,96.3
XS GIS Cut Line= 2
     1817040.407      201636.120     1817574.664      201406.540
#Sta/Elev= 30
       0 1615.15     5.0 1612.26    24.8 1605.15    44.7 1592.12    79.5 1575.55
   119.3 1551.05   134.2 1538.31   149.1 1528.64   154.1 1526.00   159.0 1524.90
   178.9 1521.99   213.7 1497.02   238.6 1485.49   263.4 1472.74   291.5 1461.22
   303.2 1458.94   306.5 1459.46   323.0 1463.73   347.9 1467.43   367.8 1475.10
   392.6 1489.31   417.5 1500.62   432.4 1508.41   457.2 1524.69   477.1 1536.04
   482.1 1538.33   497.0 1542.18   502.0 1544.35   551.7 1576.32   581.5 1590.78
#Mann= 3 , 0 , 0
       0     0.1       0   291.5   0.045       0   306.5     0.1       0
Bank Sta=   291.5,   306.5
Exp/Cntr=0.3,0.1

Type RM Length L Ch R = 1 ,5434.8,122.1,123.6,125.1
XS GIS Cut Line= 3
     1817132.669      201711.216     1817355.812      201599.645
     1817673.362      201483.782
#Sta/Elev= 30
       0 1590.18     5.0 1586.76    15.0 1581.61    34.9 1564.78    59.9 1546.58
    69.8 1537.09    79.8 1530.12    94.8 1524.42   109.8 1522.03   114.8 1520.18
   124.7 1512.92   149.7 1492.19   164.7 1482.63   189.6 1469.79   199.6 1466.77
   208.7 1465.54   209.6 1465.47   223.7 1467.30   244.5 1474.70   264.4 1484.54
   284.3 1490.90   294.2 1490.86   339.0 1494.58   373.8 1499.73   428.4 1514.19
   453.3 1522.64   478.2 1526.57   532.8 1542.66   567.6 1549.73   587.5 1550.41
#Mann= 3 , 0 , 0
       0     0.1       0   208.7   0.045       0   223.7     0.1       0
Bank Sta=   208.7,   223.7
Exp/Cntr=0.3,0.1

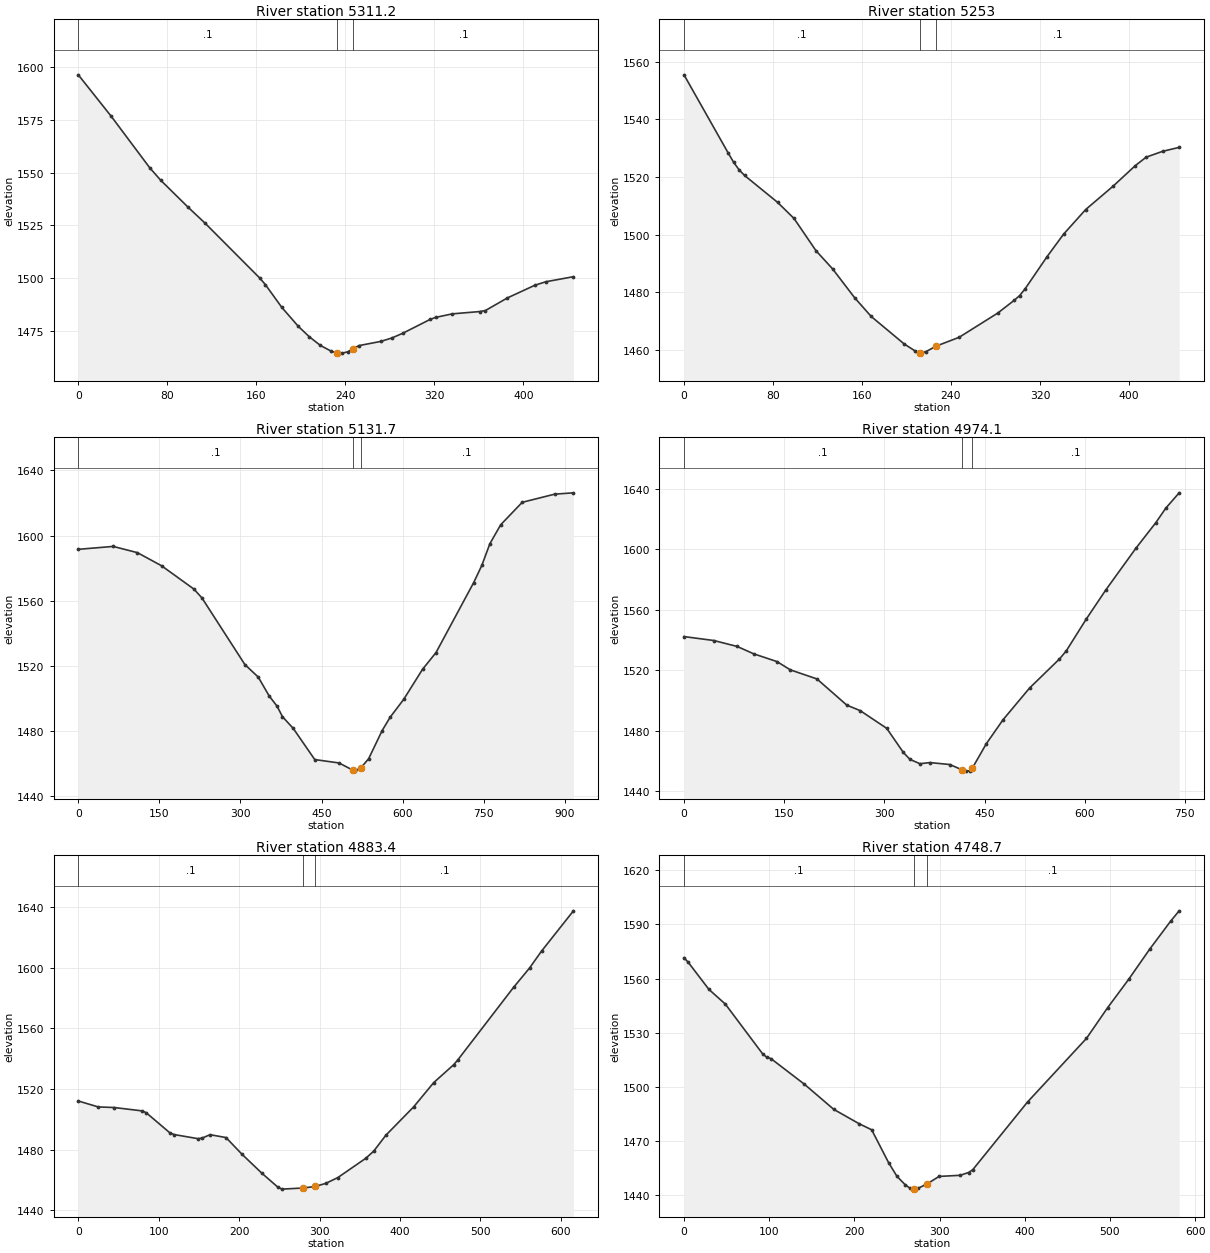
Type RM Length L Ch R = 1 ,5311.2,58.7,58.2,57.7
XS GIS Cut Line= 2
     1817130.523      201824.934     1817540.334      201651.139
#Sta/Elev= 30
       0 1596.30    29.7 1576.57    64.3 1552.18    74.2 1546.26    98.9 1533.44
   113.8 1526.07   163.2 1499.92   168.2 1496.84   183.0 1486.02   197.8 1477.06
   207.7 1472.12   217.6 1468.04   227.5 1465.25   232.3 1464.54   237.4 1464.38
   242.4 1465.03   247.3 1466.51   252.2 1467.94   272.0 1469.94   281.9 1471.57
   291.8 1473.83   316.5 1480.42   321.5 1481.35   336.3 1483.00   361.1 1484.10
   366.0 1484.58   385.8 1490.57   410.5 1496.58   420.4 1498.23   445.1 1500.61
#Mann= 3 , 0 , 0
       0     0.1       0   232.3   0.045       0   247.3     0.1       0
Bank Sta=   232.3,   247.3
Exp/Cntr=0.3,0.1

Type RM Length L Ch R = 1 ,5253,122.4,121.3,123.5
XS GIS Cut Line= 2
     1817181.080      201864.253     1817590.892      201690.458
#Sta/Elev= 30
       0 1555.45    39.6 1528.40    44.5 1525.17    49.5 1522.49    54.4 1520.54
    84.1 1511.20    98.9 1505.60   118.7 1494.38   133.5 1488.14   153.3 1478.13
   168.2 1471.62   197.8 1462.09   207.7 1459.63   211.9 1458.99   212.7 1458.87
   217.6 1459.41   226.9 1461.34   247.3 1464.36   281.9 1472.74   296.8 1477.19
   301.7 1478.84   306.6 1481.18   326.4 1492.38   341.3 1500.20   361.1 1508.71
   385.8 1516.84   405.6 1523.91   415.5 1526.89   430.3 1528.91   445.1 1530.27
#Mann= 3 , 0 , 0
       0     0.1       0   211.9   0.045       0   226.9     0.1       0
Bank Sta=   211.9,   226.9
Exp/Cntr=0.3,0.1

Type RM Length L Ch R = 1 ,5131.7,158.3,157.6,161.8
XS GIS Cut Line= 3
     1816905.383      201978.354     1817319.337      201923.632
     1817796.433      201779.108
#Sta/Elev= 30
       0 1591.53    64.6 1593.31   109.4 1589.48   154.1 1581.42   213.8 1567.14
   228.7 1561.71   308.2 1520.77   333.0 1513.05   352.9 1501.62   367.8 1495.17
   377.8 1488.73   397.7 1481.55   437.5 1462.42   482.4 1460.34   507.9 1455.91
   512.3 1455.32   522.9 1457.39   537.2 1462.95   562.1 1480.18   577.1 1488.49
   602.0 1499.36   636.9 1517.85   661.8 1528.11   731.6 1571.14   746.6 1581.67
   761.5 1594.97   781.5 1606.61   821.3 1620.39   881.2 1625.39   916.1 1626.22
#Mann= 3 , 0 , 0
       0     0.1       0   507.9   0.045       0   522.9     0.1       0
Bank Sta=   507.9,   522.9
Exp/Cntr=0.3,0.1

Type RM Length L Ch R = 1 ,4974.1,82.5,90.7,93.7
XS GIS Cut Line= 2
     1816954.583      202060.951     1817692.673      201990.146
#Sta/Elev= 30
       0 1542.18    44.8 1539.57    79.6 1535.65   104.5 1530.75   139.3 1525.63
   159.2 1520.17   199.0 1514.18   243.8 1496.84   263.8 1493.21   303.6 1481.48
   328.4 1465.58   338.4 1460.95   353.3 1458.09   368.2 1458.85   398.1 1457.55
   416.9 1453.94   423.0 1453.19   428.0 1453.46   431.9 1455.28   452.8 1471.38
   477.7 1487.15   517.5 1508.16   562.3 1527.39   572.3 1532.63   602.1 1553.57
   632.0 1573.25   676.8 1600.66   706.6 1617.56   721.6 1627.19   741.5 1637.26
#Mann= 3 , 0 , 0
       0     0.1       0   416.9   0.045       0   431.9     0.1       0
Bank Sta=   416.9,   431.9
Exp/Cntr=0.3,0.1

Type RM Length L Ch R = 1 ,4883.4,143.7,134.7,125.9
XS GIS Cut Line= 2
     1817042.553      202097.426     1817658.343      202095.280
#Sta/Elev= 30
       0 1512.10    24.8 1508.18    44.7 1507.79    79.5 1505.56    84.4 1504.38
   114.2 1490.94   119.2 1489.94   149.0 1487.21   154.0 1487.62   163.9 1489.85
   183.7 1487.96   203.6 1476.92   228.4 1464.36   248.3 1455.16   253.3 1453.90
   279.6 1454.65   294.6 1455.64   307.9 1457.72   322.8 1461.54   357.6 1474.28
   367.5 1479.03   382.4 1489.42   417.2 1508.29   442.0 1524.24   466.8 1536.02
   471.8 1539.11   541.3 1587.12   561.2 1599.91   576.1 1611.06   615.8 1637.68
#Mann= 3 , 0 , 0
       0     0.1       0   279.6   0.045       0   294.6     0.1       0
Bank Sta=   279.6,   294.6
Exp/Cntr=0.3,0.1

Type RM Length L Ch R = 1 ,4748.7,181.9,182.4,183.1
XS GIS Cut Line= 3
     1817066.722      202342.147     1817181.936      202290.367
     1817598.774      202107.898
#Sta/Elev= 30
       0 1571.54     4.9 1569.03    29.2 1554.00    48.6 1545.79    92.3 1518.25
    97.2 1516.35   102.0 1515.65   141.2 1501.48   175.8 1487.50   205.4 1479.58
   220.3 1476.18   240.1 1458.03   250.0 1450.37   259.8 1445.67   264.8 1443.97
   269.8 1443.29     270 1443.31   274.7 1443.75     285 1446.07   299.4 1450.33
   324.2 1450.95   334.0 1452.49   339.0 1454.06   403.3 1491.58   472.5 1526.84
   497.3 1543.82   522.0 1559.53   546.7 1576.27   571.4 1591.86   581.3 1597.52
#Mann= 3 , 0 , 0
       0     0.1       0     270   0.045       0     285     0.1       0
Bank Sta=     270,     285
Exp/Cntr=0.3,0.1

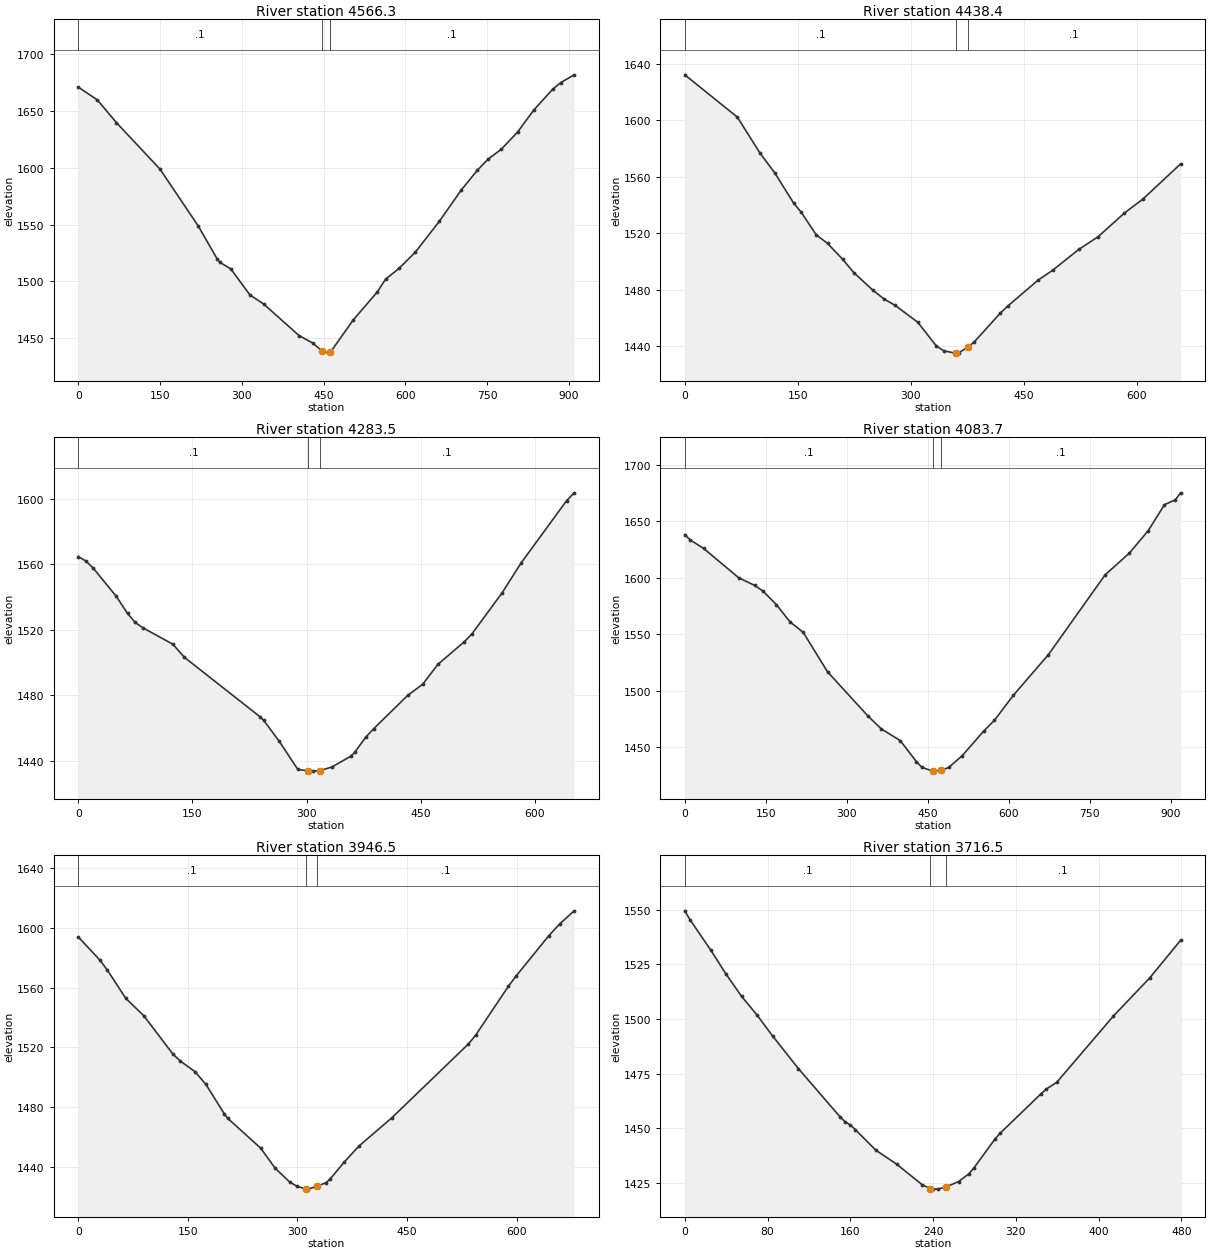
Type RM Length L Ch R = 1 ,4566.3,129.1,127.9,126.5
XS GIS Cut Line= 3
     1817003.432      202559.693     1817418.440      202373.175
     1817835.278      202190.706
#Sta/Elev= 30
       0 1670.77    35.0 1659.55    70.0 1639.55   150.0 1598.65   220.0 1548.80
   255.0 1519.64   260.0 1516.74   280.0 1510.93   315.0 1488.06   340.0 1480.22
   405.0 1452.44   430.0 1445.92   447.5 1438.78   459.9 1436.98   462.5 1437.72
   504.4 1466.06   549.0 1490.92   563.8 1501.94   588.5 1511.45   618.2 1525.52
   662.7 1552.94   702.3 1580.02   732.0 1597.57   751.8 1607.40   776.5 1616.30
   806.2 1631.33   835.8 1650.61   870.4 1668.88   885.3 1674.76   910.0 1681.62
#Mann= 3 , 0 , 0
       0     0.1       0   447.5   0.045       0   462.5     0.1       0
Bank Sta=   447.5,   462.5
Exp/Cntr=0.3,0.1

Type RM Length L Ch R = 1 ,4438.4,154,154.9,155.8
XS GIS Cut Line= 2
     1817139.105      202659.576     1817724.857      202359.190
#Sta/Elev= 30
       0 1632.33    69.8 1602.32    99.7 1576.94   119.7 1562.59   144.6 1541.27
   154.6 1534.86   174.5 1518.81   189.5 1512.81   209.4 1501.60   224.4 1492.08
   249.4 1479.70   264.3 1473.45   279.3 1468.82   309.2 1456.91   334.1 1439.98
   344.1 1436.56   359.1 1434.95   360.4 1435.03   364.0 1435.24   375.4 1439.14
   384.0 1442.71   418.9 1463.36   428.9 1468.39   468.8 1486.61   488.7 1493.86
   523.6 1508.71   548.6 1517.44   583.5 1534.22   608.4 1544.30   658.3 1569.19
#Mann= 3 , 0 , 0
       0     0.1       0   360.4   0.045       0   375.4     0.1       0
Bank Sta=   360.4,   375.4
Exp/Cntr=0.3,0.1

Type RM Length L Ch R = 1 ,4283.5,194.3,199.8,205.2
XS GIS Cut Line= 2
     1817216.347      202771.147     1817808.536      202498.655
#Sta/Elev= 30
       0 1564.83    10.0 1562.05    19.9 1557.56    49.8 1540.51    64.7 1530.04
    74.6 1524.57    84.6 1521.28   124.4 1511.18   139.3 1503.23   238.8 1466.85
   243.8 1464.58   263.7 1452.14   288.6 1434.61   302.5 1433.75   308.5 1433.57
   317.5 1433.92   333.4 1436.07   358.3 1442.71   363.3 1445.02   378.2 1454.51
   388.1 1459.40   432.9 1479.83   452.8 1486.74   472.7 1498.83   507.6 1512.76
   517.5 1517.48   557.3 1542.71   582.2 1560.93   641.9 1598.95   651.9 1603.78
#Mann= 3 , 0 , 0
       0     0.1       0   302.5   0.045       0   317.5     0.1       0
Bank Sta=   302.5,   317.5
Exp/Cntr=0.3,0.1

Type RM Length L Ch R = 1 ,4083.7,139.3,137.2,129.7
XS GIS Cut Line= 3
     1817101.948      202916.162     1817655.105      202809.106
     1818008.782      202781.927
#Sta/Elev= 30
       0 1638.22    10.0 1633.60    34.9 1626.09    99.7 1600.08   129.6 1593.23
   144.6 1588.32   169.5 1576.30   194.5 1561.08   219.4 1551.57   264.3 1516.64
   339.0 1477.50   364.0 1465.93   398.9 1455.66   428.8 1437.03   438.8 1432.02
   458.7 1428.54   459.2 1428.56   474.2 1429.12   488.6 1431.81   513.6 1442.20
   553.4 1464.02   573.4 1473.67   608.4 1495.82   673.3 1531.87   778.2 1602.58
   823.2 1621.94   858.2 1641.90   888.2 1664.90   908.2 1669.19   918.1 1675.40
#Mann= 3 , 0 , 0
       0     0.1       0   459.2   0.045       0   474.2     0.1       0
Bank Sta=   459.2,   474.2
Exp/Cntr=0.3,0.1

Type RM Length L Ch R = 1 ,3946.5,234.8,230,230.7
XS GIS Cut Line= 2
     1817272.211      203040.206     1817926.622      202859.974
#Sta/Elev= 30
       0 1593.94    30.0 1578.21    39.9 1571.62    64.9 1552.88    89.8 1541.08
   129.8 1515.31   139.8 1510.77   159.7 1503.76   174.7 1495.18   199.6 1475.66
   204.6 1472.43   249.6 1452.52   269.5 1439.03   289.5 1429.78   299.5 1426.91
   311.3 1425.20   314.4 1425.05   326.3 1426.87   339.4 1429.44   344.4 1431.62
   364.3 1443.33   384.3 1453.95   429.2 1472.84   534.0 1522.25   544.0 1528.22
   588.9 1561.00   598.9 1567.53   643.8 1594.63   658.8 1602.58   678.8 1611.45
#Mann= 3 , 0 , 0
       0     0.1       0   311.3   0.045       0   326.3     0.1       0
Bank Sta=   311.3,   326.3
Exp/Cntr=0.3,0.1

Type RM Length L Ch R = 1 ,3716.5,115.3,120.5,125.5
XS GIS Cut Line= 2
     1817424.472      203290.385     1817842.865      203056.513
#Sta/Elev= 30
       0 1549.50     5.0 1545.46    25.0 1531.59    39.9 1520.51    54.9 1510.34
    69.9 1501.75    84.9 1492.18   109.8 1477.27   149.8 1455.32   154.8 1452.98
   159.8 1451.51   164.8 1449.36   184.7 1439.88   204.7 1433.54   229.7 1424.00
   237.3 1422.34   239.7 1422.07   244.6 1422.13   252.3 1423.00   264.6 1425.53
   274.6 1429.05   279.6 1431.86   299.6 1444.85   304.6 1447.56   344.5 1465.80
   349.5 1467.92   359.5 1470.95   414.4 1501.36   449.4 1518.77   479.3 1536.02
#Mann= 3 , 0 , 0
       0     0.1       0   237.3   0.045       0   252.3     0.1       0
Bank Sta=   237.3,   252.3
Exp/Cntr=0.3,0.1

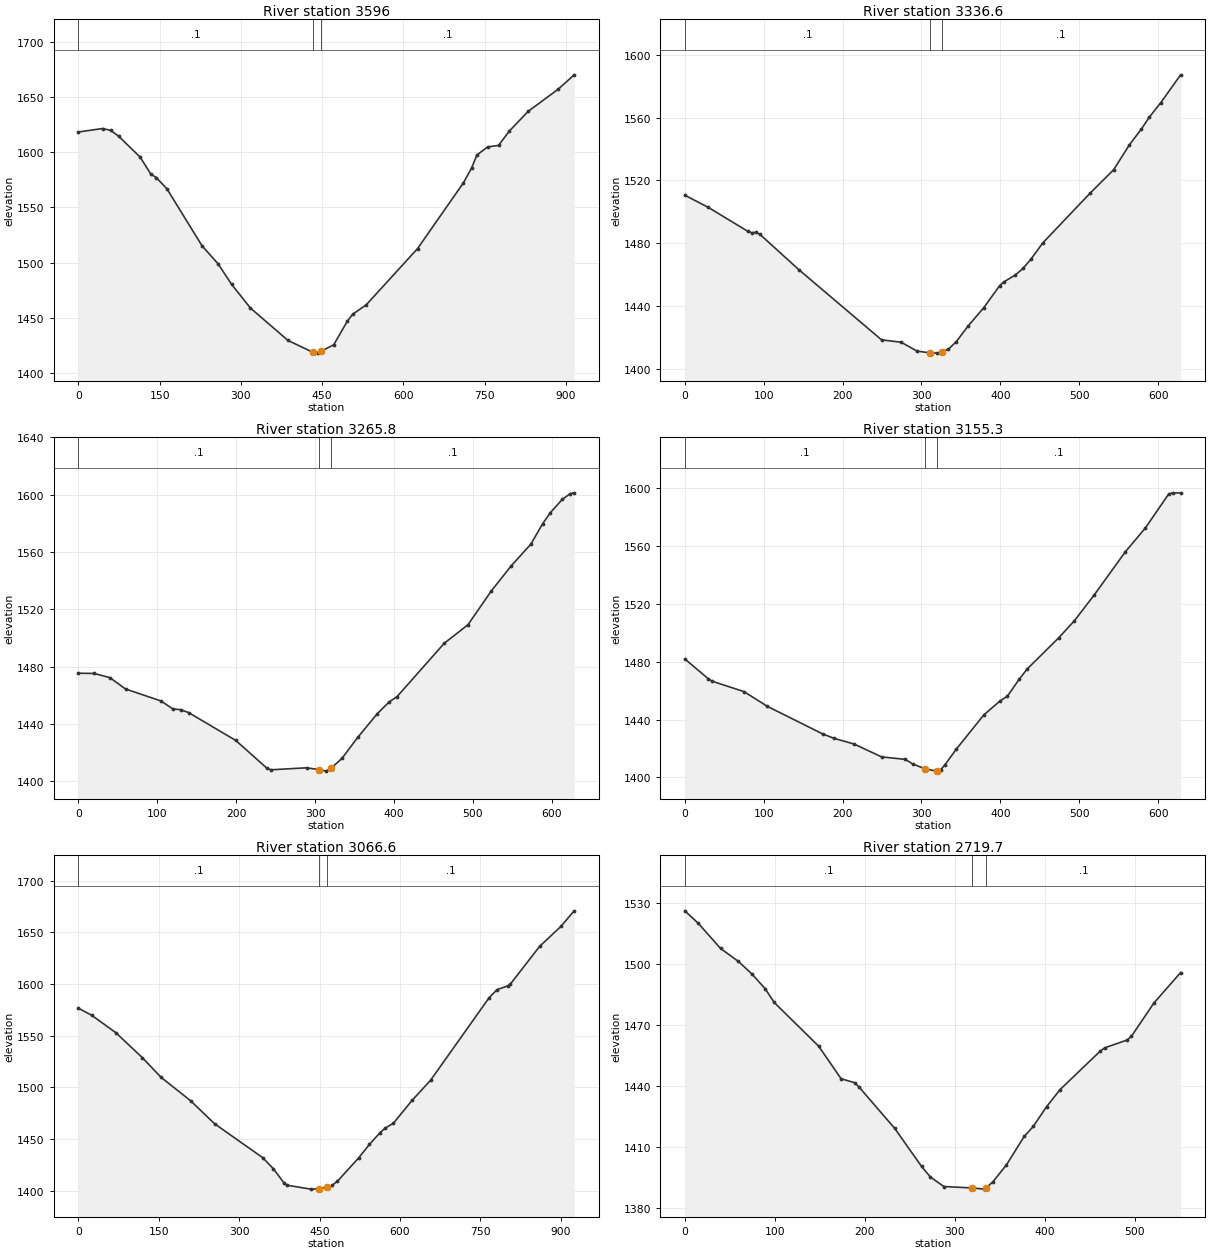
Type RM Length L Ch R = 1 ,3596,254.1,259.4,264.5
XS GIS Cut Line= 3
     1817264.357      203402.724     1817707.855      203274.803
     1818124.603      203095.106
#Sta/Elev= 30
       0 1618.30    44.7 1621.44    59.6 1619.81    74.4 1614.48   114.2 1595.53
   134.0 1580.04   143.9 1577.10   163.8 1566.72   228.3 1515.37   258.1 1498.94
   282.9 1480.49   317.6 1459.06   387.1 1429.67   432.5 1419.10   441.7 1418.20
   447.5 1419.75   471.6 1425.80   496.5 1447.01   506.5 1453.40   531.4 1461.84
   626.2 1512.76   710.9 1572.26   725.9 1585.56   735.9 1597.52   755.8 1604.83
   775.8 1606.15   795.7 1619.14   830.6 1637.02   885.5 1656.85   915.4 1670.03
#Mann= 3 , 0 , 0
       0     0.1       0   432.5   0.045       0   447.5     0.1       0
Bank Sta=   432.5,   447.5
Exp/Cntr=0.3,0.1

Type RM Length L Ch R = 1 ,3336.6,71.1,70.8,70.8
XS GIS Cut Line= 2
     1817418.035      203547.858     1818044.553      203498.509
#Sta/Elev= 30
       0 1510.62    29.9 1502.82    79.8 1487.68    84.8 1486.76    89.8 1486.96
    94.8 1485.91   144.6 1463.24   249.4 1418.64   274.3 1417.12   294.3 1411.51
   310.8 1410.36   319.2 1410.20   325.8 1410.82   334.2 1412.73   344.2 1417.52
   359.1 1427.45   379.1 1439.16   399.0 1453.03   404.0 1455.37   419.0 1459.87
   429.0 1464.19   438.9 1470.05   453.9 1480.34   513.7 1511.87   543.7 1526.88
   563.6 1542.67   578.6 1552.53   588.6 1560.10   603.5 1569.53   628.5 1587.14
#Mann= 3 , 0 , 0
       0     0.1       0   310.8   0.045       0   325.8     0.1       0
Bank Sta=   310.8,   325.8
Exp/Cntr=0.3,0.1

Type RM Length L Ch R = 1 ,3265.8,110.5,110.5,110.5
XS GIS Cut Line= 2
     1817432.613      203617.452     1818059.131      203568.104
#Sta/Elev= 30
       0 1475.47    20.0 1475.30    39.9 1472.42    59.8 1464.49   104.7 1456.14
   119.7 1450.59   129.7 1450.04   139.7 1448.04   199.5 1428.62   239.4 1409.09
   244.4 1408.13   289.3 1409.52   305.5 1408.23   314.2 1407.20   320.5 1409.29
   334.2 1416.11   354.1 1430.68   379.1 1447.36   394.0 1455.44   404.0 1459.17
   463.9 1496.39   493.8 1509.22   523.7 1533.00   548.6 1550.26   573.6 1565.47
   588.6 1579.78   598.5 1587.54   613.5 1596.70   623.5 1600.69   628.5 1601.26
#Mann= 3 , 0 , 0
       0     0.1       0   305.5   0.045       0   320.5     0.1       0
Bank Sta=   305.5,   320.5
Exp/Cntr=0.3,0.1

Type RM Length L Ch R = 1 ,3155.3,95,88.7,87.2
XS GIS Cut Line= 2
     1817435.812      203727.817     1818062.330      203678.468
#Sta/Elev= 30
       0 1481.98    29.9 1468.21    34.9 1466.51    74.8 1459.42   104.7 1449.16
   174.6 1430.11   189.5 1426.96   214.5 1423.10   249.4 1414.20   279.3 1412.46
   289.3 1409.21   304.5 1405.90   319.2 1404.32   319.5 1404.37   324.2 1405.20
   329.2 1408.28   344.2 1419.57   379.1 1443.29   399.0 1452.63   409.0 1456.29
   424.0 1468.02   433.9 1474.98   473.8 1496.51   493.8 1508.39   518.7 1526.07
   558.6 1556.30   583.6 1572.48   613.5 1596.26   618.5 1596.98   628.5 1596.90
#Mann= 3 , 0 , 0
       0     0.1       0   304.5   0.045       0   319.5     0.1       0
Bank Sta=   304.5,   319.5
Exp/Cntr=0.3,0.1

Type RM Length L Ch R = 1 ,3066.6,349,346.9,340
XS GIS Cut Line= 3
     1817291.424      203832.336     1817832.137      203781.730
     1818199.419      203677.522
#Sta/Elev= 30
       0 1576.68    24.9 1569.78    69.8 1553.01   119.6 1528.69   154.4 1509.75
   209.3 1487.20   254.1 1464.89   343.8 1432.15   363.7 1421.47   383.6 1407.70
   388.6 1405.52   433.5 1401.68   448.1 1402.02   463.1 1403.51   473.3 1405.28
   483.3 1409.30   523.2 1432.08   543.1 1444.98   562.9 1456.30   572.8 1460.81
   587.7 1465.36   622.4 1487.40   657.1 1506.97   766.2 1586.70   781.1 1594.60
   800.9 1598.13   805.9 1599.92   860.4 1636.34   900.1 1655.63   924.9 1670.76
#Mann= 3 , 0 , 0
       0     0.1       0   448.1   0.045       0   463.1     0.1       0
Bank Sta=   448.1,   463.1
Exp/Cntr=0.3,0.1

Type RM Length L Ch R = 1 ,2719.7,232.9,220.2,207.5
XS GIS Cut Line= 2
     1817561.845      204171.152     1818070.246      203958.748
#Sta/Elev= 30
       0 1526.37    14.9 1520.26    39.7 1507.84    59.6 1501.43    74.5 1495.28
    89.4 1487.95    99.3 1481.23   148.9 1459.59   173.7 1443.60   188.6 1441.69
   193.6 1439.54   233.3 1419.13   263.1 1400.38   273.0 1395.13   287.9 1390.48
   319.6 1389.78   332.6 1389.20   334.6 1389.73   342.5 1392.87   357.4 1401.12
   377.2 1415.19   387.2 1420.09   402.1 1429.87   417.0 1438.26   461.6 1457.20
   466.6 1458.84   491.4 1462.67   496.4 1464.59   521.2 1480.87   551.0 1495.97
#Mann= 3 , 0 , 0
       0     0.1       0   319.6   0.045       0   334.6     0.1       0
Bank Sta=   319.6,   334.6
Exp/Cntr=0.3,0.1

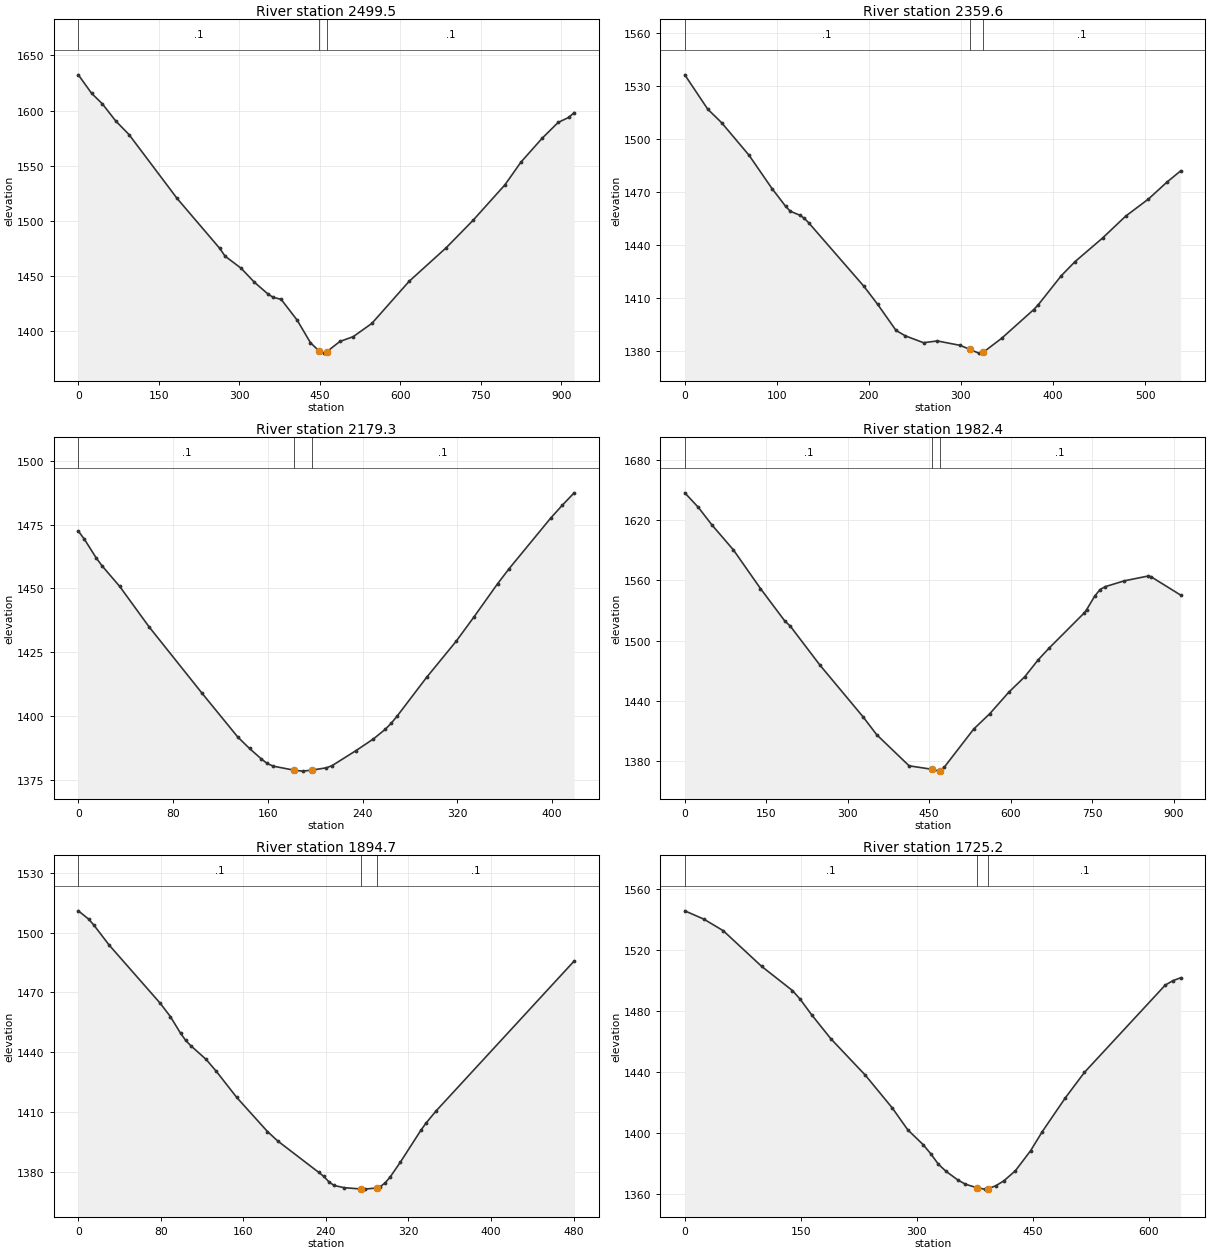
Type RM Length L Ch R = 1 ,2499.5,140.1,139.9,139.7
XS GIS Cut Line= 3
     1817709.967      204593.768     1818016.660      204152.920
     1818317.351      203909.375
#Sta/Elev= 30
       0 1632.39    24.9 1615.53    44.8 1606.09    69.6 1590.62    94.5 1578.23
   184.0 1520.40   263.6 1475.06   273.5 1468.04   303.3 1457.14   328.2 1444.37
   353.0 1433.93   363.0 1430.73   377.9 1428.96   407.8 1410.06   432.6 1389.62
   448.1 1382.37   457.5 1380.18   463.1 1381.48   487.3 1390.72   512.2 1395.10
   547.0 1407.11   616.4 1445.24   685.9 1475.86   735.5 1500.49   795.0 1532.71
   824.8 1553.26   864.4 1574.95   894.2 1589.27   914.1 1593.85   924.0 1598.18
#Mann= 3 , 0 , 0
       0     0.1       0   448.1   0.045       0   463.1     0.1       0
Bank Sta=   448.1,   463.1
Exp/Cntr=0.3,0.1

Type RM Length L Ch R = 1 ,2359.6,180.4,180.3,180.2
XS GIS Cut Line= 2
     1817913.670      204547.712     1818218.347      204103.571
#Sta/Elev= 30
       0 1536.08    24.9 1516.68    39.9 1509.06    69.8 1490.59    94.8 1471.70
   109.7 1461.60   114.7 1458.89   124.7 1456.74   129.7 1454.97   134.6 1452.39
   194.5 1416.50   209.5 1406.26   229.4 1391.54   239.4 1388.47   259.3 1384.55
   274.3 1385.56   299.2 1383.04   309.4 1380.84   319.2 1378.66   324.4 1379.23
   344.1 1387.02   379.0 1403.28   384.0 1406.05   408.9 1422.41   423.9 1430.42
   453.8 1443.76   478.8 1456.10   503.7 1465.85   523.6 1475.32   538.6 1481.74
#Mann= 3 , 0 , 0
       0     0.1       0   309.4   0.045       0   324.4     0.1       0
Bank Sta=   309.4,   324.4
Exp/Cntr=0.3,0.1

Type RM Length L Ch R = 1 ,2179.3,184.4,196.9,210.8
XS GIS Cut Line= 2
     1818074.591      204582.042     1818317.045      204240.890
#Sta/Elev= 30
       0 1472.45     5.0 1469.33    15.0 1462.00    19.9 1458.89    34.9 1450.77
    59.8 1434.85   104.6 1408.77   134.5 1391.75   144.5 1387.21   154.5 1383.10
   159.4 1381.34   164.4 1380.29   182.2 1378.69   189.3 1378.33   197.2 1378.73
   209.3 1379.63   214.2 1380.49   234.2 1386.33   249.1 1390.96   259.1 1394.75
   264.1 1397.11   269.1 1399.91   294.0 1415.12   318.9 1429.25   333.8 1438.70
   353.8 1451.76   363.7 1457.77   398.6 1477.49   408.6 1482.65   418.5 1487.45
#Mann= 3 , 0 , 0
       0     0.1       0   182.2   0.045       0   197.2     0.1       0
Bank Sta=   182.2,   197.2
Exp/Cntr=0.3,0.1

Type RM Length L Ch R = 1 ,1982.4,87.7,87.7,86.2
XS GIS Cut Line= 3
     1817882.056      204763.373     1818299.233      204574.821
     1818727.612      204421.134
#Sta/Elev= 30
       0 1647.06    24.9 1632.66    49.8 1615.24    89.6 1590.27   139.3 1551.92
   184.1 1519.66   194.1 1514.62   248.8 1475.79   328.4 1424.24   353.3 1406.60
   413.0 1375.66   454.6 1372.25   467.7 1370.38   469.6 1370.76   477.6 1374.21
   532.0 1412.25   561.7 1427.58   596.3 1448.72   626.0 1464.27   650.7 1481.07
   670.5 1492.54   734.8 1527.33   739.8 1530.89   754.6 1544.25   764.5 1550.91
   774.4 1553.83   809.0 1559.53   853.6 1564.41   858.5 1563.61   912.9 1545.42
#Mann= 3 , 0 , 0
       0     0.1       0   454.6   0.045       0   469.6     0.1       0
Bank Sta=   454.6,   469.6
Exp/Cntr=0.3,0.1

Type RM Length L Ch R = 1 ,1894.7,169.1,169.5,170
XS GIS Cut Line= 2
     1818076.737      204764.419     1818518.732      204575.605
#Sta/Elev= 30
       0 1510.94     9.9 1506.82    14.9 1503.90    29.7 1493.88    79.3 1464.62
    89.2 1457.91    99.1 1449.54   104.1 1445.92   109.0 1443.30   123.9 1436.40
   133.8 1430.40   153.6 1417.31   183.3 1400.25   193.2 1395.54   232.9 1379.80
   237.8 1377.79   242.8 1375.06   247.8 1373.19   257.7 1372.08   274.2 1371.40
   277.5 1371.35   289.2 1371.94   292.4 1372.48   297.3 1374.46   302.3 1377.46
   312.2 1384.93   332.0 1400.85   336.9 1404.41   346.8 1410.59   480.6 1485.76
#Mann= 3 , 0 , 0
       0     0.1       0   274.2   0.045       0   289.2     0.1       0
Bank Sta=   274.2,   289.2
Exp/Cntr=0.3,0.1

Type RM Length L Ch R = 1 ,1725.2,81.3,81,81
XS GIS Cut Line= 2
     1818008.077      204961.815     1818602.411      204721.506
#Sta/Elev= 30
       0 1545.75    24.8 1540.26    49.7 1532.71    99.4 1509.31   139.2 1493.45
   149.1 1487.82   164.0 1477.58   188.8 1461.87   233.6 1437.85   268.4 1416.38
   288.2 1402.17   308.1 1392.43   318.0 1386.42   328.0 1379.49   337.9 1374.84
   352.8 1369.31   362.8 1366.46   377.2 1364.19   387.6 1363.21   392.2 1363.42
   402.5 1365.54   412.5 1368.62   427.4 1375.24   447.3 1388.54   462.2 1400.91
   492.0 1423.07   516.8 1439.83   621.2 1497.03   631.1 1499.93   641.1 1501.83
#Mann= 3 , 0 , 0
       0     0.1       0   377.2   0.045       0   392.2     0.1       0
Bank Sta=   377.2,   392.2
Exp/Cntr=0.3,0.1

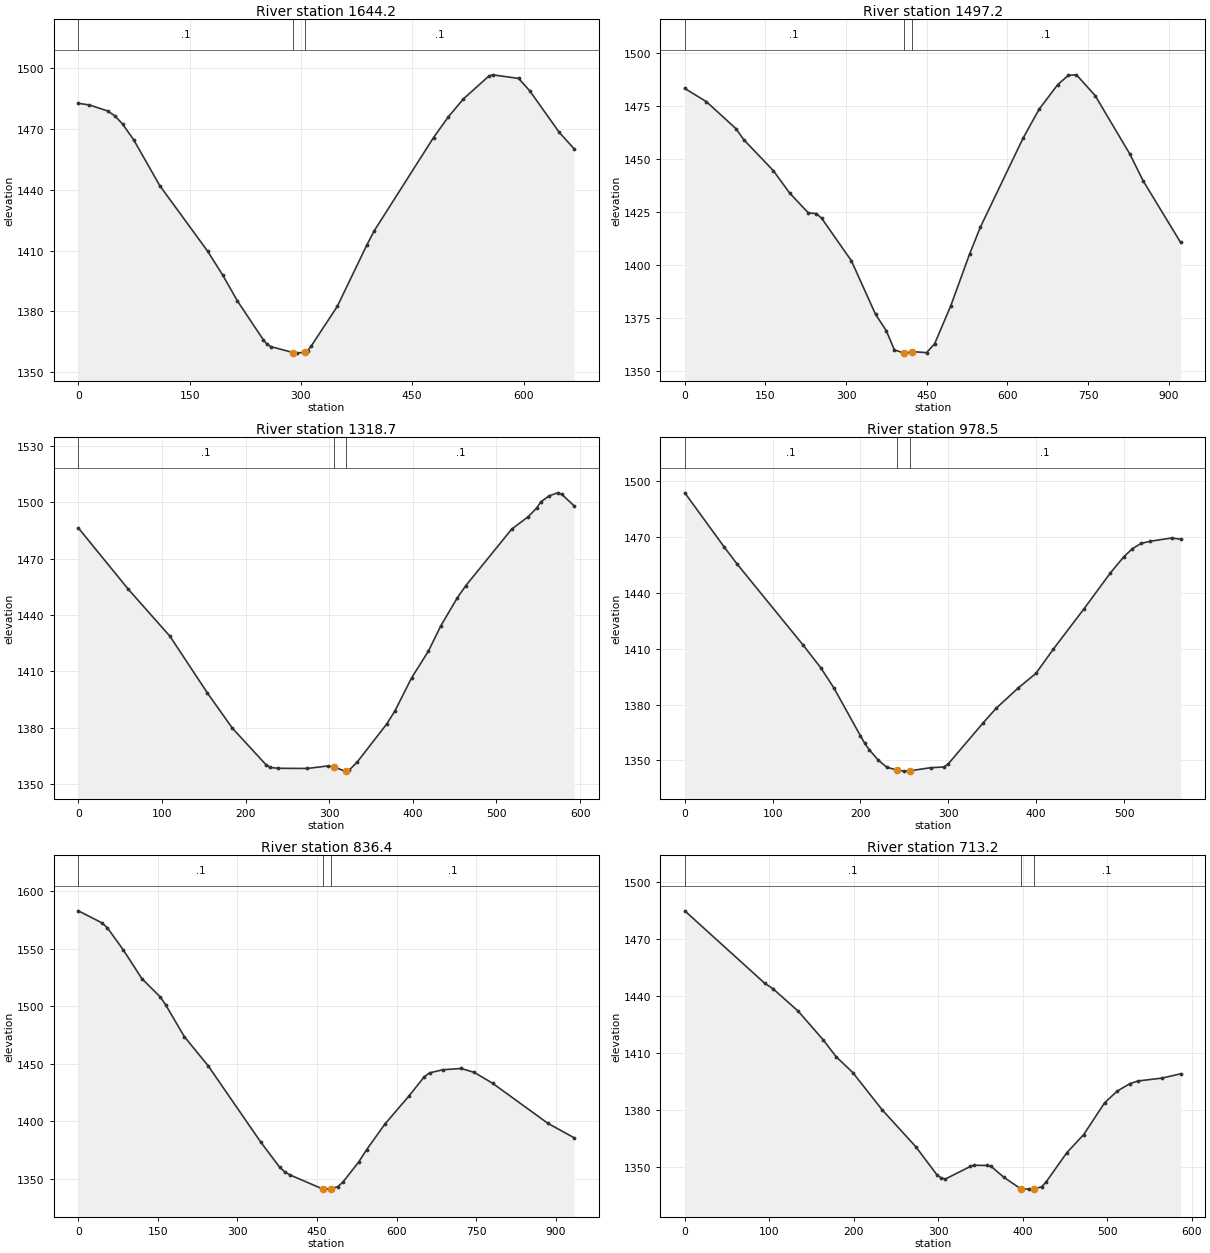
Type RM Length L Ch R = 1 ,1644.2,140.9,146.9,152.8
XS GIS Cut Line= 2
     1818113.212      205004.727     1818733.293      204755.836
#Sta/Elev= 30
       0 1482.75    15.0 1481.92    39.9 1478.90    49.9 1476.32    59.8 1472.41
    74.8 1464.60   109.7 1442.12   174.5 1409.59   194.5 1397.96   214.4 1385.15
   249.3 1365.98   254.3 1363.74   259.3 1362.62   289.9 1359.61   294.2 1359.39
   304.9 1359.87   309.2 1360.66   314.1 1363.04   349.0 1382.47   388.9 1412.84
   398.9 1419.87   478.7 1465.84   498.6 1476.01   518.6 1484.78   553.5 1496.28
   558.5 1496.80   593.4 1495.01   608.3 1488.93   648.2 1468.36   668.2 1460.25
#Mann= 3 , 0 , 0
       0     0.1       0   289.9   0.045       0   304.9     0.1       0
Bank Sta=   289.9,   304.9
Exp/Cntr=0.3,0.1

Type RM Length L Ch R = 1 ,1497.2,188.9,178.5,167.3
XS GIS Cut Line= 3
     1817969.297      205092.145     1818514.441      205021.892
     1818848.331      204856.731
#Sta/Elev= 30
       0 1483.44    40.0 1477.24    94.9 1464.51   109.9 1459.19   164.9 1444.56
   194.9 1434.07   229.8 1424.65   244.8 1424.34   254.8 1422.04   309.8 1402.06
   354.8 1376.74   374.8 1369.00   389.8 1359.96     407 1358.48   409.7 1358.42
     422 1359.16   449.7 1358.65   464.7 1362.85   494.7 1380.79   529.7 1405.24
   549.6 1417.86   629.1 1459.94   658.9 1473.60   693.7 1485.29   713.6 1489.65
   728.5 1489.88   763.2 1480.09   827.8 1452.44   852.6 1439.76   922.2 1410.69
#Mann= 3 , 0 , 0
       0     0.1       0     407   0.045       0     422     0.1       0
Bank Sta=     407,     422
Exp/Cntr=0.3,0.1

Type RM Length L Ch R = 1 ,1318.7,348.6,340.3,332.6
XS GIS Cut Line= 2
     1818205.473      205352.316     1818690.381      205011.164
#Sta/Elev= 30
       0 1486.26    59.8 1453.65   109.6 1428.66   154.4 1398.52   184.3 1379.79
   224.2 1360.53   229.2 1358.96   239.2 1358.52   274.0 1358.43   298.9 1359.81
   305.6 1359.23   318.9 1357.01   320.6 1357.18   323.8 1357.50   333.8 1362.03
   368.7 1382.02   378.6 1389.03   398.6 1406.65   418.5 1420.70   433.5 1434.26
   453.4 1449.27   463.4 1455.62   518.2 1485.62   538.1 1492.28   548.0 1496.79
   553.0 1500.10   563.0 1503.27   573.0 1504.91   577.9 1504.20   592.9 1497.99
#Mann= 3 , 0 , 0
       0     0.1       0   305.6   0.045       0   320.6     0.1       0
Bank Sta=   305.6,   320.6
Exp/Cntr=0.3,0.1

Type RM Length L Ch R = 1 ,978.5,141.8,142.1,142.3
XS GIS Cut Line= 2
     1818511.557      205639.283     1818839.835      205180.123
#Sta/Elev= 30
       0 1493.63    45.0 1464.46    59.9 1455.22   134.9 1411.80   154.8 1399.74
   169.8 1388.85   199.8 1363.37   204.8 1359.26   209.8 1355.88   219.8 1350.38
   229.8 1346.41   241.2 1344.88   249.8 1344.28   256.2 1344.44   279.7 1346.12
   294.7 1346.48   299.7 1348.07   339.7 1370.24   354.6 1378.10   379.6 1388.94
   399.6 1396.68   419.6 1409.82   454.6 1431.51   484.5 1450.67   499.5 1459.20
   509.5 1463.65   519.5 1466.48   529.5 1467.62   554.4 1469.40   564.4 1468.73
#Mann= 3 , 0 , 0
       0     0.1       0   241.2   0.045       0   256.2     0.1       0
Bank Sta=   241.2,   256.2
Exp/Cntr=0.3,0.1

Type RM Length L Ch R = 1 ,836.4,126.2,123.2,121.4
XS GIS Cut Line= 3
     1818439.629      205808.972     1818761.732      205525.143
     1819059.795      205116.841
#Sta/Elev= 30
       0 1582.83    44.9 1572.29    54.9 1568.02    84.9 1548.85   119.8 1523.96
   154.8 1507.91   164.7 1501.21   199.7 1473.73   244.6 1448.44   344.4 1381.79
   379.4 1360.40   389.4 1356.16   399.4 1353.55   460.7 1341.41   464.0 1341.28
   475.7 1341.71   488.8 1343.32   498.7 1347.29   528.4 1364.69   543.3 1375.36
   578.0 1397.76   622.6 1421.69   652.3 1438.86   662.2 1442.16   687.0 1444.89
   721.7 1445.99   746.5 1442.58   781.2 1433.12   885.3 1398.38   934.8 1385.85
#Mann= 3 , 0 , 0
       0     0.1       0   460.7   0.045       0   475.7     0.1       0
Bank Sta=   460.7,   475.7
Exp/Cntr=0.3,0.1

Type RM Length L Ch R = 1 ,713.2,345.9,351.4,355.5
XS GIS Cut Line= 3
     1818660.522      205906.529     1818959.601      205448.709
     1818980.306      205414.199
#Sta/Elev= 30
       0 1484.59    94.5 1446.54   104.4 1443.62   134.2 1431.86   164.1 1416.60
   179.0 1407.96   198.9 1399.53   233.7 1379.92   273.4 1360.58   298.3 1345.90
   303.2 1344.16   308.2 1343.46   338.0 1350.12   343.0 1350.78   357.9 1350.65
   362.9 1350.12   377.8 1344.44     398 1338.32   407.6 1338.21     413 1338.29
   422.6 1339.47   427.5 1341.76   452.4 1357.42   472.3 1366.88   497.1 1383.62
   512.0 1389.76   527.0 1393.69   536.9 1395.11   564.7 1396.60   587.1 1398.85
#Mann= 3 , 0 , 0
       0     0.1       0     398   0.045       0     413     0.1       0
Bank Sta=     398,     413
Exp/Cntr=0.3,0.1