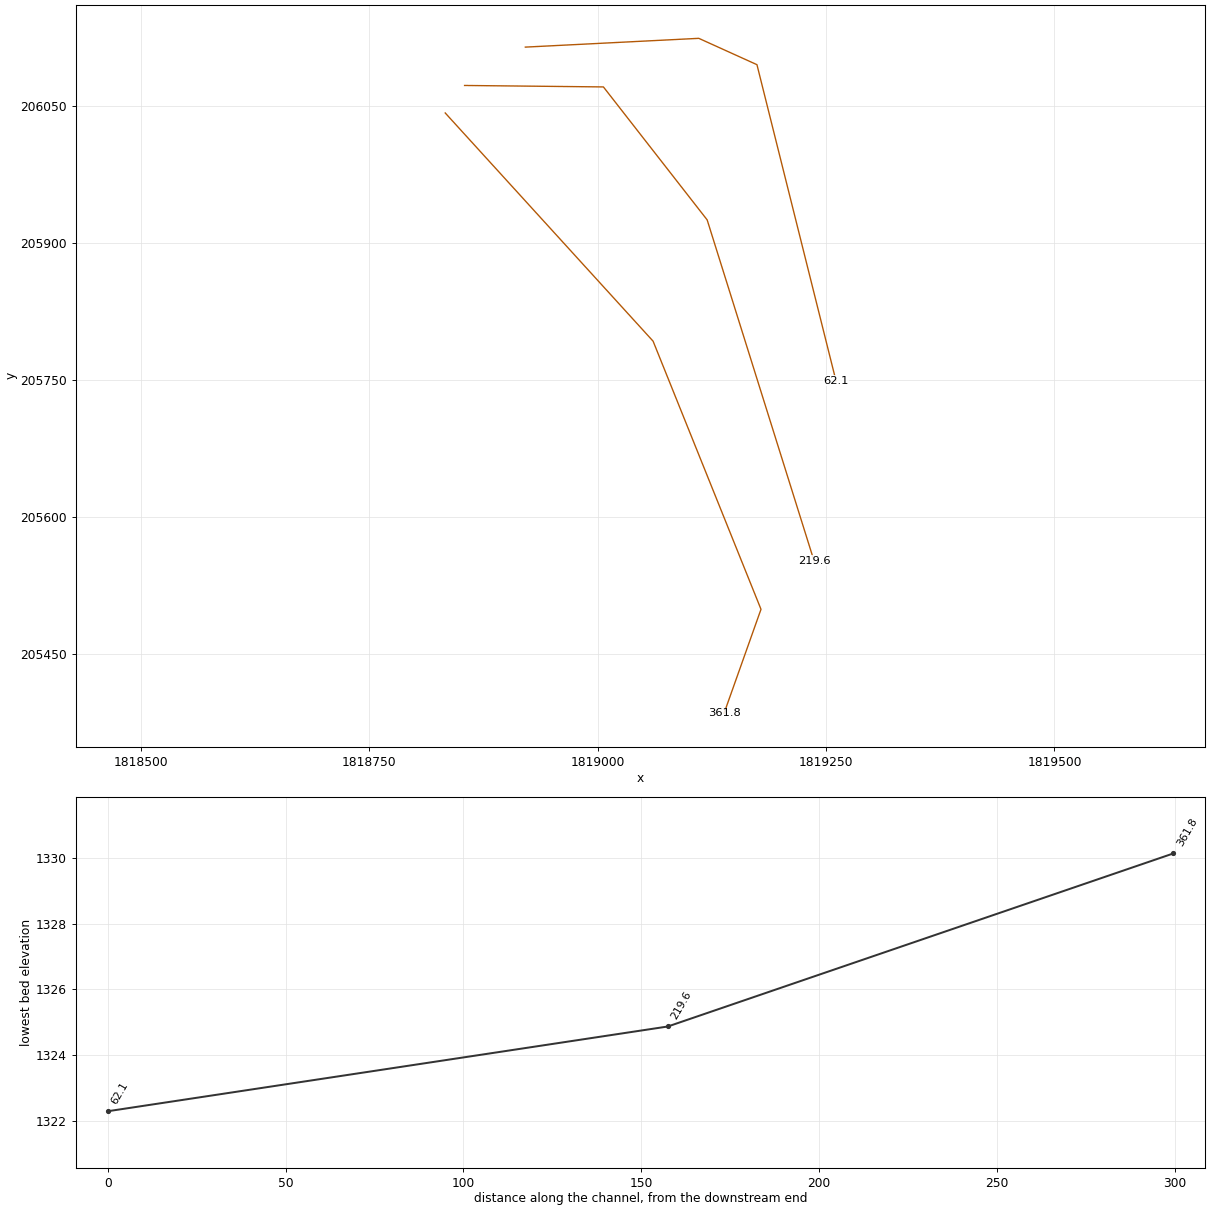
HEC-RAS study LambertBr1.prj: LambertBr1

--- LambertBr1.g01 (geometry) --- (continued)

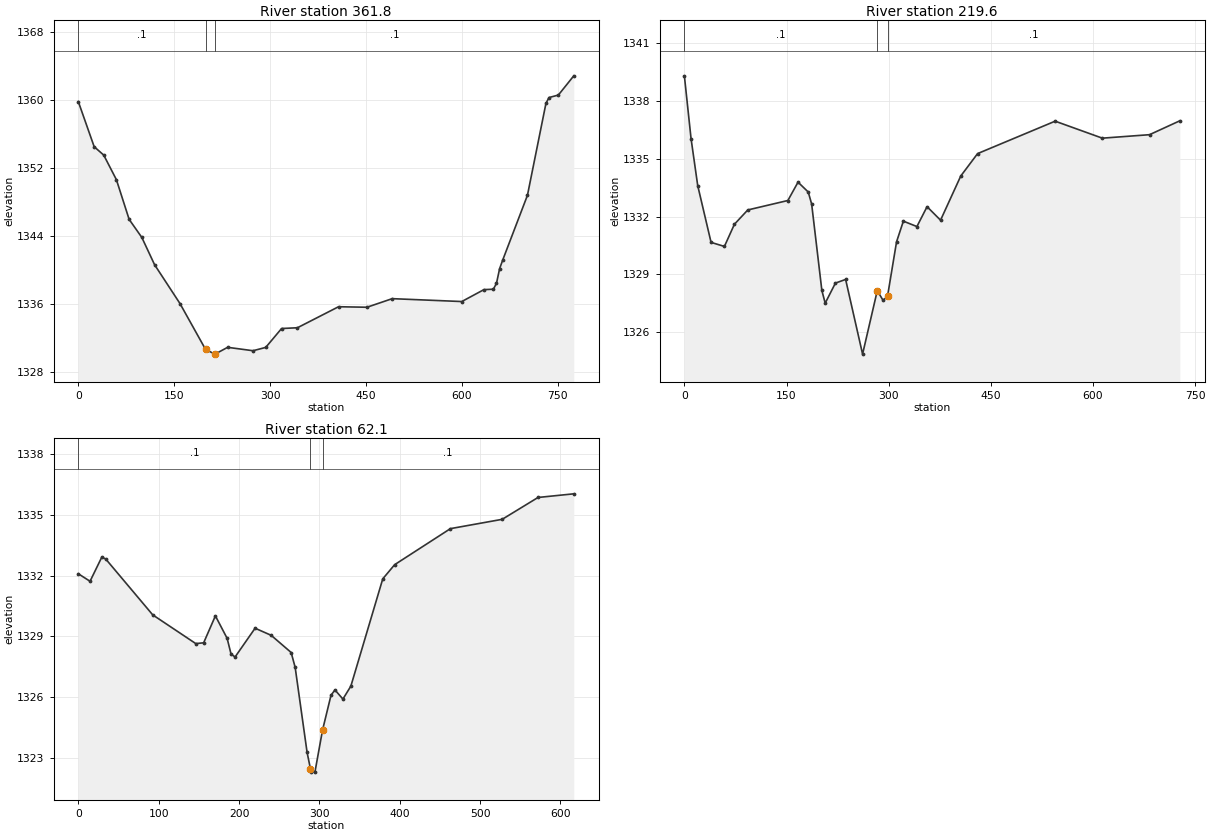
Type RM Length L Ch R = 1 ,361.8,143.5,142.2,141.4
XS GIS Cut Line= 4
     1818833.115      206041.879     1819060.654      205792.079
     1819178.753      205498.612     1819138.286      205384.680
#Sta/Elev= 30
       0 1359.82    24.8 1354.52    39.8 1353.53    59.6 1350.64    79.5 1345.98
    99.4 1343.85   119.3 1340.65   159.0 1336.09   199.1 1330.69   213.7 1330.14
   214.1 1330.15   233.6 1330.94   273.3 1330.54   293.2 1330.93   318.0 1333.15
   342.8 1333.24   407.1 1335.71   451.6 1335.65   491.1 1336.66   599.9 1336.32
   634.5 1337.72   649.3 1337.77   654.2 1338.46   659.1 1340.19   663.9 1341.19
   702.6 1348.80   731.6 1359.62   736.4 1360.30   751.0 1360.59   775.1 1362.85
#Mann= 3 , 0 , 0
       0     0.1       0   199.1   0.045       0   214.1     0.1       0
Bank Sta=   199.1,   214.1
Exp/Cntr=0.3,0.1

Type RM Length L Ch R = 1 ,219.6,167.1,157.5,117.6
XS GIS Cut Line= 4
     1818854.319      206071.990     1819006.271      206070.390
     1819119.835      205924.836     1819236.806      205551.683
#Sta/Elev= 30
       0 1339.29     9.8 1336.04    19.6 1333.60    39.2 1330.66    58.8 1330.45
    73.5 1331.60    93.1 1332.34   152.0 1332.83   166.9 1333.78   181.9 1333.27
   186.9 1332.65   201.9 1328.17   206.8 1327.51   221.8 1328.55   236.8 1328.74
   261.7 1324.87   283.3 1328.16   291.7 1327.66   298.3 1327.86   311.6 1330.69
   321.6 1331.76   341.5 1331.48   356.4 1332.51   376.2 1331.81   405.9 1334.10
   430.6 1335.26   544.5 1336.94   613.8 1336.06   683.1 1336.24   727.6 1336.96
#Mann= 3 , 0 , 0
       0     0.1       0   283.3   0.045       0   298.3     0.1       0
Bank Sta=   283.3,   298.3
Exp/Cntr=0.3,0.1

Type RM Length L Ch R = 1 ,62.1,39.5,62.1,114.8
XS GIS Cut Line= 4
     1818920.822      206113.966     1819110.653      206123.578
     1819174.330      206094.743     1819260.835      205748.723
#Sta/Elev= 30
       0 1332.09    14.6 1331.72    29.2 1332.91    34.1 1332.82    92.6 1330.06
   146.2 1328.64   156.0 1328.68   170.6 1330.01   185.2 1328.90   190.1 1328.12
   195.1 1327.98   220.0 1329.40   240.0 1329.05   264.9 1328.20   269.9 1327.46
   284.7 1323.27   288.9 1322.45   289.7 1322.29   294.6 1322.32   303.9 1324.36
   314.5 1326.09   319.4 1326.35   329.3 1325.90   339.2 1326.54   378.9 1331.84
   393.7 1332.54   463.1 1334.32   527.5 1334.78   572.1 1335.86   616.6 1336.04
#Mann= 3 , 0 , 0
       0     0.1       0   288.9   0.045       0   303.9     0.1       0
Bank Sta=   288.9,   303.9
Exp/Cntr=0.3,0.1